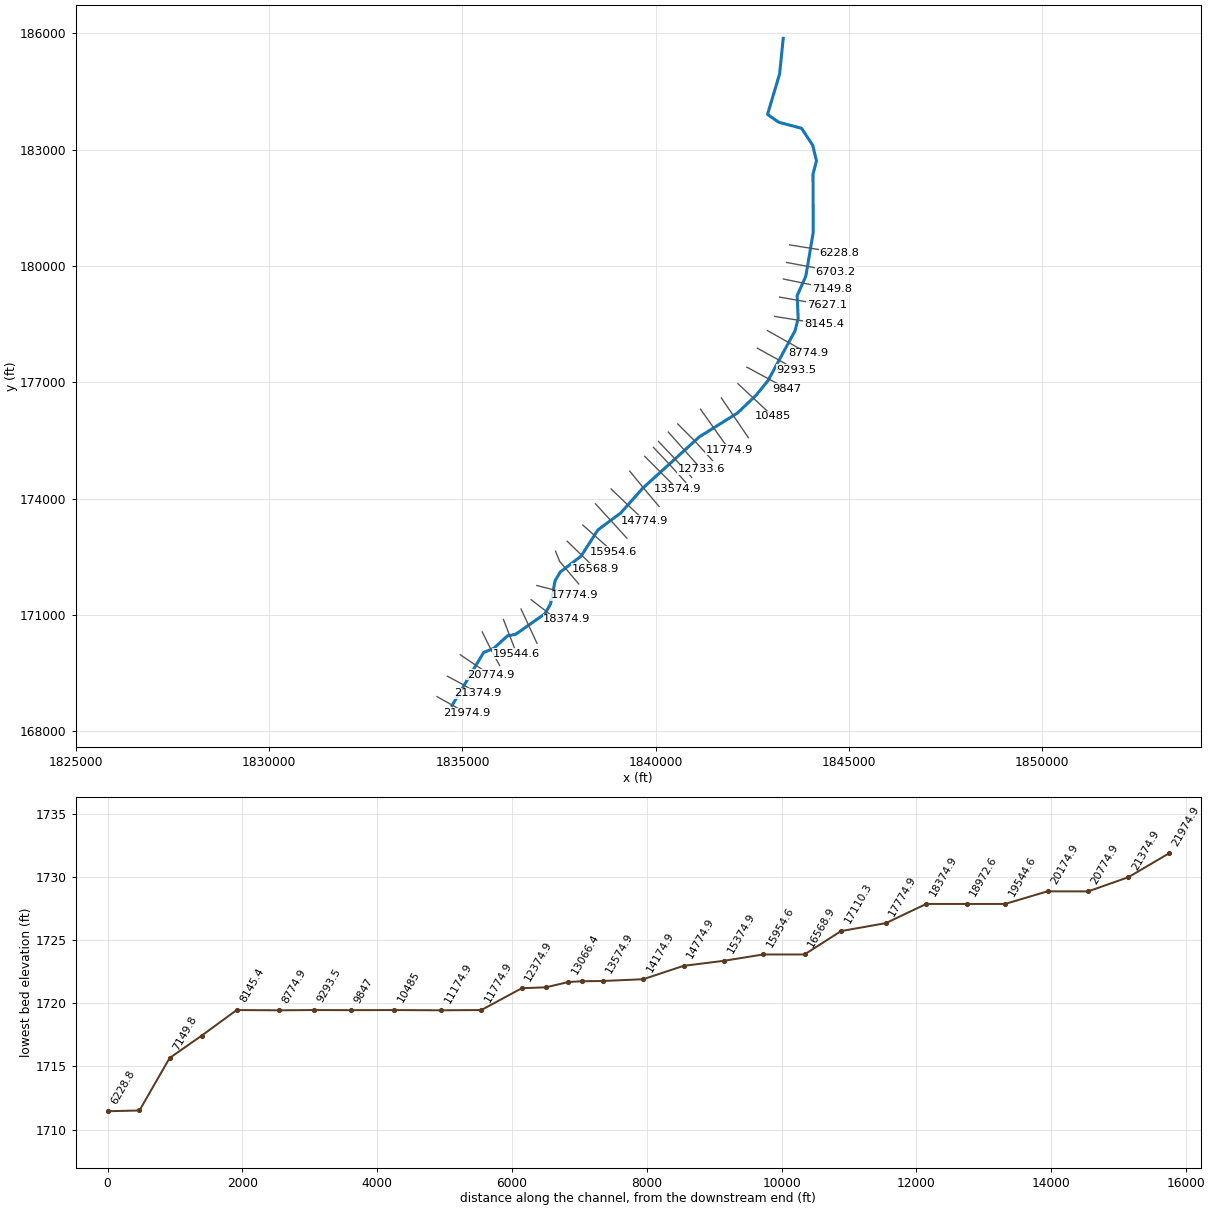
--- TYGARTVR2.prj (project) ---

Proj Title=TYGARTVR2
Current Plan=p01
Default Exp/Contr=0,0
English Units
Geom File=g01
Flow File=f01
Plan File=p01
BEGIN DESCRIPTION:
END DESCRIPTION:
DSS Export Rating Curves= 0
DSS Export Rating Curve Sorted= 0
DSS Export Volume Flow Curves= 0
DXF OffsetX= 0
DXF OffsetY= 0
DXF ScaleX= 0
DXF ScaleY= 0

--- TYGARTVR2.p01 (plan) ---

Plan Title=Floodplain
Program Version=4.00
Geom File=g01
Flow File=f01
K Sum by GR=0
Std Step Tol=0.01
Critical Tol=0.01
Num of Std Step Trials=20
Max Error Tol=0.3
Flow Tol Ratio=0.001
Split Flow NTrial=30
Split Flow Tol=0.02
Split Flow Ratio=0.02
Log Output Level=0
Friction Slope Method=1
Unsteady Friction Slope Method=2
Unsteady Bridges Friction Slope Method=1
Global Log Level=0
CheckData=False
Run HTab=0
Run UNet=0
Run PostProcess=0
UNET Theta=0
UNET Theta Warmup=0
UNET ZTol=0
UNET ZSATol=0
UNET MxIter=0
UNET MaxInSteps=0
UNET DtIC=0
UNET DtMin=0
UNET MaxCRTS=0
UNET WFStab=0
UNET SFStab=0
UNET WFX=0
UNET SFX=0
UNET DSS MLevel=0
UNET DZMax Abort=0
UNET Convert EG Bridges=0
UNET Use Existing IB Tables=0
UNET Froude Limit=0
UNET Froude Power=0
Write IC File=0
Echo Input=False
Echo Output=False
Write Detailed=0

--- TYGARTVR2.f01 (steady flow) ---

Flow Title=NFF Regression Equation
Program Version=4.10
Number of Profiles= 1
Profile Names=P100yr
River Rch & RM=TYGARTVR2,Main            ,21974.9
23172.94
River Rch & RM=TYGARTVR2,Main            ,186.1
 23801.5
Boundary for River Rch & Prof#=TYGARTVR2,Main            , 1
Up Type= 0
Dn Type= 1
Dn Known WS=1706.5
DSS Import GetInterval= 0
DSS Import GetPeak= 0
DSS Import FillOption= 0

--- TYGARTVR2.g01 (geometry) ---

Geom Title=USGS 10m DEM
Program Version=4.10

River Reach=TYGARTVR2       ,Main
Reach XY= 30
     1834731.393      168661.758     1835547.406      170028.709
     1835815.079      170137.858     1836163.314      170457.506
     1836373.814      170496.487     1837132.654      171026.636
     1837278.185      171276.117     1837397.718      171881.782
     1837529.868      172103.636     1838066.599      172511.456
      1838507.06      173191.597       1839093.6      173625.916
      1839669.05      174269.897     1841132.156      175592.669
     1842117.088      176205.978     1842596.916      176663.291
     1842905.141      177039.822     1843605.689      178327.499
     1843686.743      178651.417     1843660.756      179230.942
     1843884.174      179736.177     1844074.614      180852.292
     1844071.275      182370.973     1844160.493      182709.094
     1844063.564      183110.901     1843775.101      183550.092
     1843185.181      183706.018      1842894.12      183908.722
     1843205.972      184950.828     1843300.078      185870.781

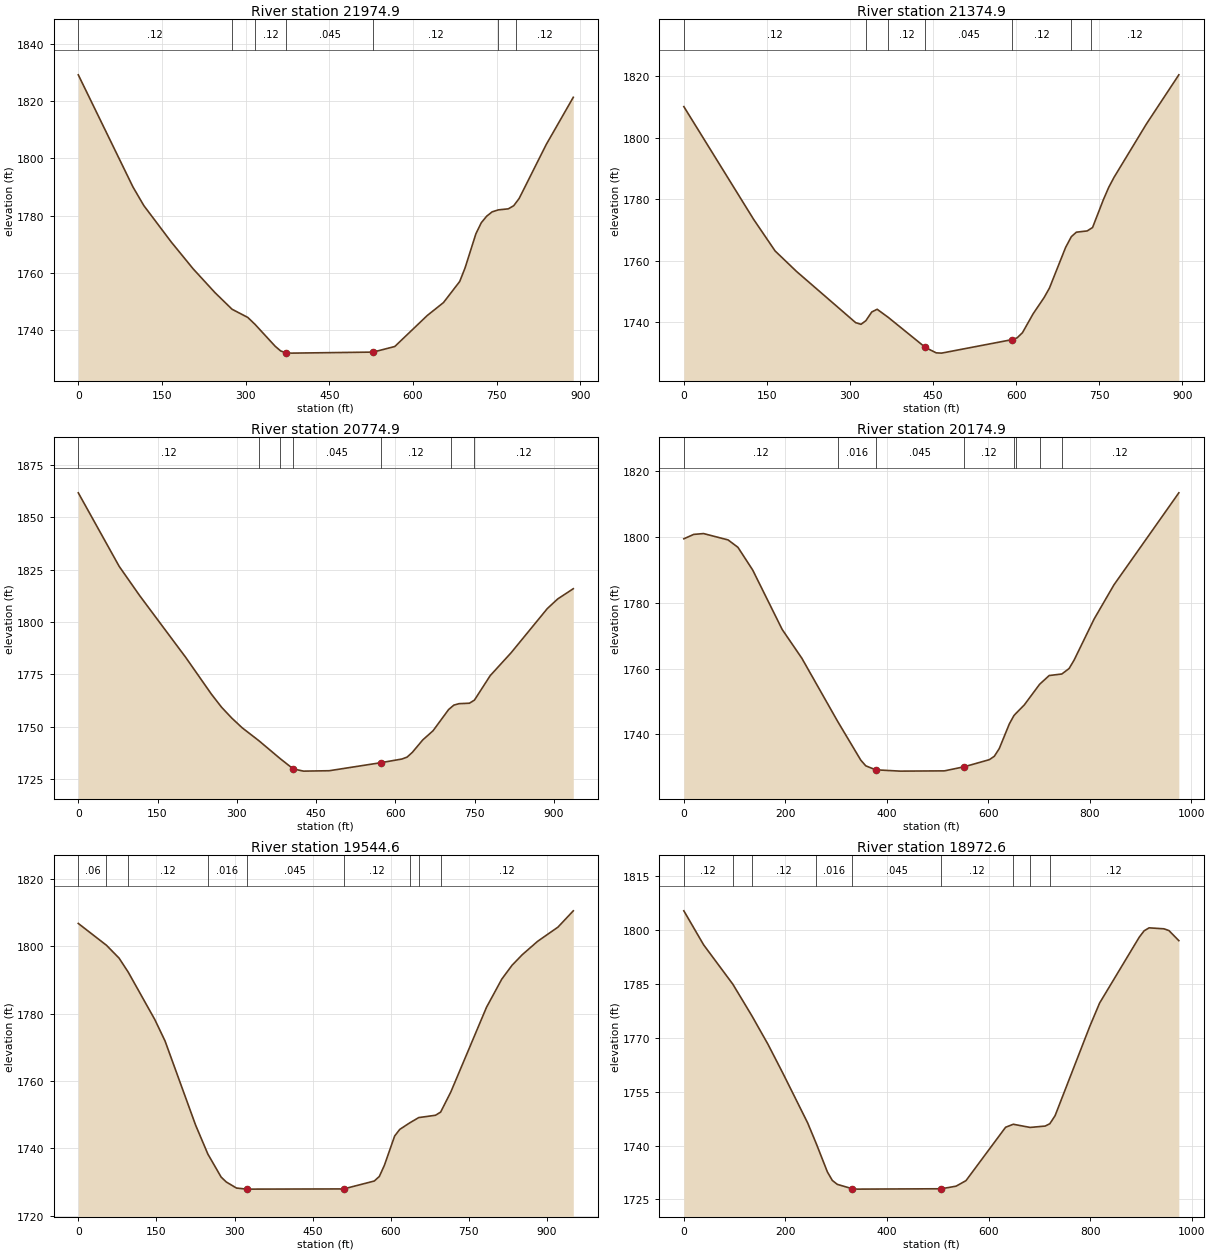
Type RM Length L Ch R = 1 ,21974.9 ,599.3,600,598.8
XS GIS Cut Line= 3
     1834342.316      168890.069     1834736.262      168670.493
      1835117.44      168458.033
#Sta/Elev= 30
       0 1829.28      98 1790.03   117.6 1783.48   166.7 1770.75   205.9 1761.37
   245.1 1753.03  275.631747.225   303.9 1744.35  316.751741.952     353 1734.26
   362.8 1732.62   372.6 1731.93   382.4 1731.86   528.6 1732.22   567.4 1734.18
   625.6 1745.03   654.7 1749.56   683.8 1756.94   693.4 1761.69   712.8 1773.64
   722.5 1777.51   732.2 1779.81   741.9 1781.31  753.211782.012     771 1782.37
   780.7 1783.48  785.261784.674   790.4 1786.02   838.9 1804.89   887.4 1821.41
#Mann= 7 ,-1 , 0
       0     .12       0  275.63    .016       0  316.75     .12       0
   372.6    .045       0   528.6     .12       0  753.21    .016       0
  785.26     .12       0
Bank Sta=372.6,528.6
XS Rating Curve= 0 ,0
Exp/Cntr=0.3,0.1

Type RM Length L Ch R = 1 ,21374.9 ,604,600,598.5
XS GIS Cut Line= 3
     1834610.314      169416.661     1835020.783      169197.261
      1835388.32      168977.093
#Sta/Elev= 30
       0 1810.07     126 1773.45   164.8 1763.18   203.6  1756.5   310.3 1739.88
     320 1739.34  328.731740.528   339.4 1743.36   349.1 1744.23  369.131741.601
   436.3 1731.81   455.7 1730.07   465.4 1729.98     592 1734.34   601.8 1734.94
   611.5 1736.62     631 1742.83   650.4 1747.98   660.2  1751.1   689.4 1764.32
  699.731767.811   708.9 1769.28   728.3 1769.68  735.141770.455   738.1 1770.79
   757.5 1779.78   767.3 1783.85     777 1787.14   835.4 1804.45   893.9  1820.4
#Mann= 7 ,-1 , 0
       0     .12       0  328.73    .016       0  369.13     .12       0
   436.3    .045       0     592     .12       0  699.73    .016       0
  735.14     .12       0
Bank Sta=436.3,592
XS Rating Curve= 0 ,0
Exp/Cntr=0.3,0.1

Type RM Length L Ch R = 1 ,20774.9 ,619.8,600,581
XS GIS Cut Line= 3
     1834944.689       169970.37     1835329.609      169709.408
     1835724.666      169451.507
#Sta/Elev= 30
       0 1861.73    77.5 1826.58   116.3  1812.6   203.5 1783.09   251.9 1765.62
   271.3 1759.32   290.6 1754.15     310 1749.57  341.541743.425   382.31734.778
   406.9 1729.89   426.3 1728.85   474.9 1729.04   573.2  1732.9   612.5 1734.63
   622.3 1735.55   632.1 1737.78   651.8 1743.72   671.4 1748.13   700.9 1758.27
   706.21759.394   710.8 1760.37   720.6 1761.06   740.2 1761.27  749.741762.764
   779.6 1774.46   818.9  1785.3   887.7 1806.48   907.3 1811.06   936.8 1815.94
#Mann= 7 ,-1 , 0
       0     .12       0  341.54    .016       0   382.3     .12       0
   406.9    .045       0   573.2     .12       0   706.2    .016       0
  749.74     .12       0
Bank Sta=406.9,573.2
XS Rating Curve= 0 ,0
Exp/Cntr=0.3,0.1

Type RM Length L Ch R = 1 ,20174.9 ,633.9,630.3,624.2
XS GIS Cut Line= 3
     1835511.931      170558.326      1835740.31      170098.208
     1835962.383      169693.079
#Sta/Elev= 30
       0 1799.41    19.4 1800.74    38.8    1801    87.2 1799.07   106.6 1796.83
   135.7 1789.93   193.8 1771.89   232.6 1763.14  303.121743.984   348.9 1732.17
   358.6 1730.47     378 1729.26   426.4 1728.86   513.7 1728.94     553  1730.2
   602.2 1732.34     612 1733.37   621.8 1735.73   641.5 1743.17  650.631745.732
  654.681746.399     671 1748.95  701.151755.211   720.1 1757.89  745.051758.353
   759.4 1760.02   769.2 1762.56   808.6 1775.02   847.9 1785.45   975.7 1813.37
#Mann= 8 ,-1 , 0
       0     .12       0  303.12    .016       0     378    .045       0
     553     .12       0  650.63     .08       0  654.68     .12       0
  701.15    .016       0  745.05     .12       0
Bank Sta=378,553
XS Rating Curve= 0 ,0
Exp/Cntr=0.3,0.1

Type RM Length L Ch R = 1 ,19544.6 ,571,572.1,573.3
XS GIS Cut Line= 2
     1836061.412      170880.755     1836403.451      169994.088
#Sta/Elev= 30
       0 1806.79   54.131800.303    78.4 1796.47   95.921792.318     147 1778.21
   166.6 1771.86   225.3 1746.86  248.831738.269   274.3 1731.43   284.1 1729.99
   303.7 1728.18   323.3 1727.86   509.5 1727.92   568.2 1730.26     578 1731.62
   587.8 1734.97   607.4 1743.64   617.2  1745.6  636.011747.516  653.621749.114
   685.8  1749.8   695.71750.747   715.2  1756.7   783.8 1781.89   813.2 1790.27
   832.8 1794.36   852.4  1797.5   881.8 1801.47     921  1805.7   950.4 1810.54
#Mann= 9 ,-1 , 0
       0     .06       0   54.13    .016       0   95.92     .12       0
  248.83    .016       0   323.3    .045       0   509.5     .12       0
  636.01     .08       0  653.62    .016       0   695.7     .12       0
Bank Sta=323.3,509.5
XS Rating Curve= 0 ,0
Exp/Cntr=0.3,0.1

Type RM Length L Ch R = 1 ,18972.6 ,578.4,597.7,615.7
XS GIS Cut Line= 2
     1836515.443      171150.146     1836928.231      170267.094
#Sta/Elev= 30
       0 1805.39      39 1795.91    96.51784.945  133.651776.228   165.7 1768.21
     195 1760.16   243.7 1746.35  260.781740.544   282.7 1732.65   292.4 1730.28
   302.2 1729.19   331.4 1727.98   341.2 1727.86   506.9 1727.96   536.1 1728.68
   555.6 1730.22   633.6 1745.09  648.731745.932  681.971745.047   711.6 1745.43
  720.751746.081   731.1 1748.32   799.3 1773.16   818.8 1779.71   896.8 1798.04
   906.5 1799.83   916.3 1800.65   945.5 1800.38   955.3 1799.89   974.8 1797.08
#Mann= 9 ,-1 , 0
       0     .12       0    96.5    .016       0  133.65     .12       0
  260.78    .016       0   331.4    .045       0   506.9     .12       0
  648.73     .06       0  681.97    .016       0  720.75     .12       0
Bank Sta=331.4,506.9
XS Rating Curve= 0 ,0
Exp/Cntr=0.3,0.1

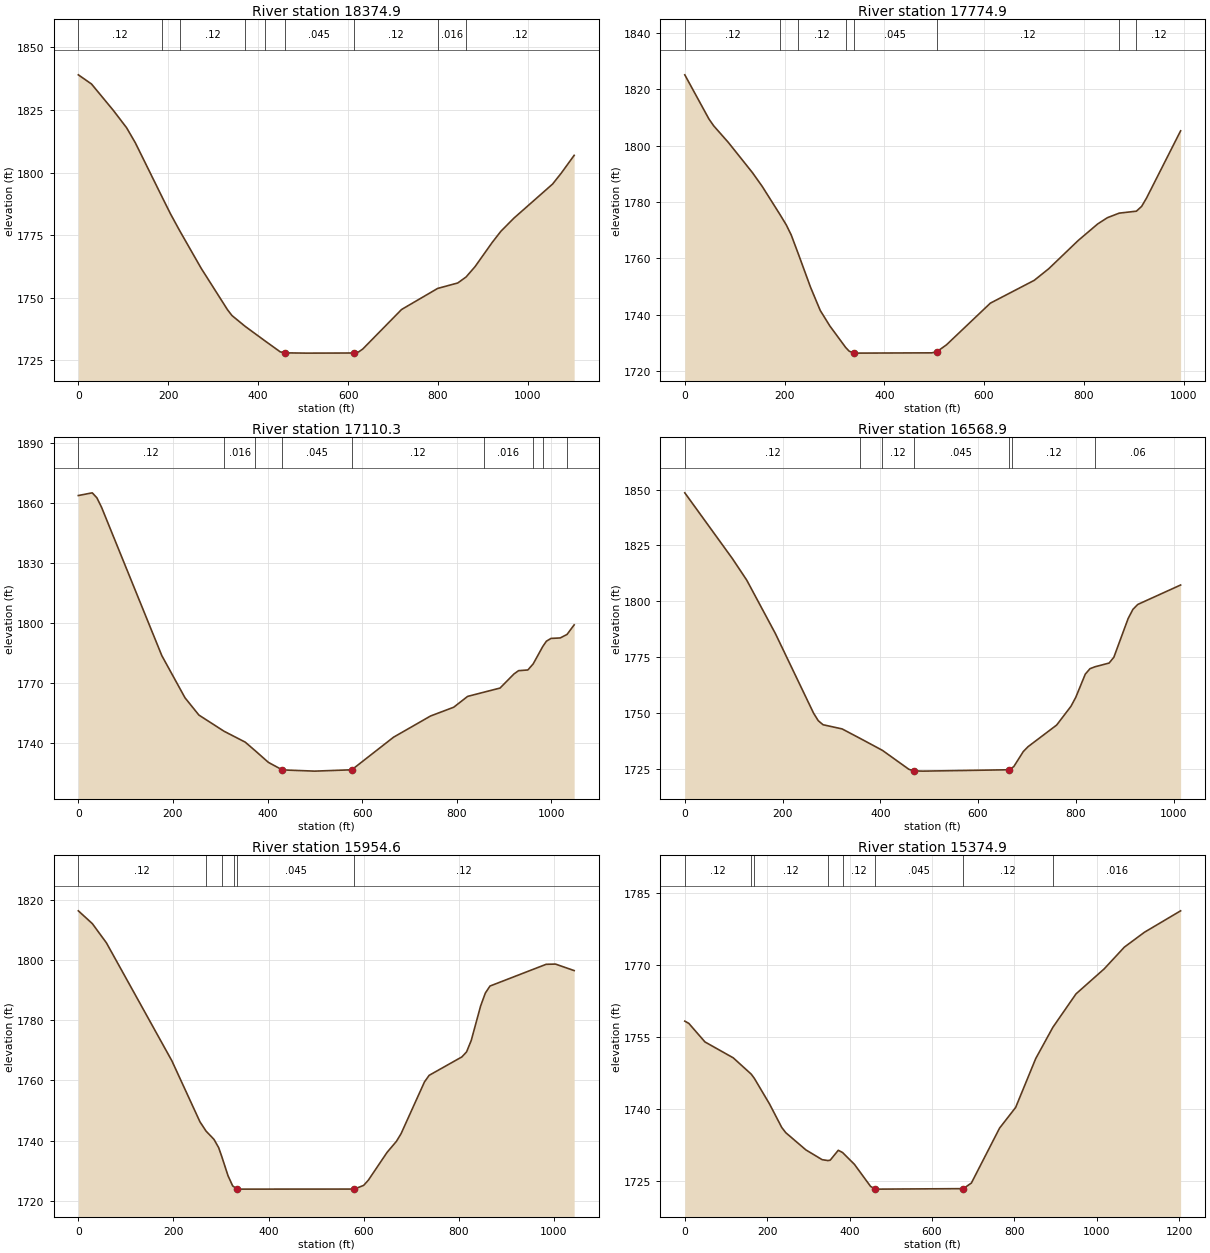
Type RM Length L Ch R = 1 ,18374.9 ,584.8,600,616.2
XS GIS Cut Line= 4
     1836775.635      171391.445     1837178.193      171082.294
     1837416.135      170887.615      1837703.93      170887.143
#Sta/Elev= 30
       0 1839.01    29.3 1835.35    78.1 1824.75   107.4 1817.86   126.9 1811.82
  186.961789.978     205 1783.48  225.561776.716   273.3 1761.72   331.9 1745.16
   341.6 1742.89  371.011738.555  415.691732.679     449 1728.38   458.8 1727.97
   507.6 1727.86   613.2 1727.91   622.9 1728.29   632.5 1729.47   718.9 1745.28
  799.211753.702   843.8 1755.87  862.411758.268   882.2 1762.36   920.5 1772.06
   939.7  1776.5   968.5 1781.72  1054.8 1795.38    1074 1799.72  1102.8 1806.85
#Mann= 9 ,-1 , 0
       0     .12       0  186.96    .016       0  225.56     .12       0
  371.01    .016       0  415.69     .12       0   458.8    .045       0
   613.2     .12       0  799.21    .016       0  862.41     .12       0
Bank Sta=458.8,613.2
XS Rating Curve= 0 ,0
Exp/Cntr=0.3,0.1

Type RM Length L Ch R = 1 ,17774.9 ,687.8,664.6,641.4
XS GIS Cut Line= 3
     1836925.105      171756.682     1837338.423      171650.649
     1837887.588      171507.887
#Sta/Elev= 30
       0  1825.1    48.5  1809.4    58.2 1806.95    87.3 1801.11   135.8 1790.35
   155.2 1785.51  191.071775.459   203.6  1771.8   213.4 1768.26  227.711761.514
   252.1 1749.72   271.5 1741.51   290.9 1735.96   322.61728.335   329.7 1727.01
   339.4 1726.34   495.2 1726.44     505  1726.8   524.5 1729.26   612.6 1744.07
   700.6 1752.17     730 1756.34   788.7  1766.3   827.8 1772.18   847.4 1774.41
  870.941776.018  905.421776.714   915.9 1778.41   925.6 1781.32   994.1 1805.23
#Mann= 8 ,-1 , 0
       0     .12       0  191.07    .016       0  227.71     .12       0
   322.6    .016       0   339.4    .045       0     505     .12       0
  870.94    .016       0  905.42     .12       0
Bank Sta=339.4,505
XS Rating Curve= 0 ,0
Exp/Cntr=0.3,0.1

Type RM Length L Ch R = 1 ,17110.3 ,537.8,541.4,545.1
XS GIS Cut Line= 3
     1837407.887      172642.625     1837514.494      172379.069
     1838008.903      171796.721
#Sta/Elev= 30
       0 1863.84    29.4  1865.2    39.2 1862.71      49 1858.01   176.5  1783.6
   225.5 1762.47   254.9 1753.81  307.961745.712   352.9 1740.23  374.271735.864
   401.8  1730.1   431.2 1726.32   499.8 1725.71   578.1 1726.38   666.3  1742.7
   744.6 1753.34   793.6 1757.74     823 1763.17  856.851765.236   891.5 1767.34
   920.9  1774.4   930.7 1776.07   950.3 1776.41   961.61779.465   981.91788.193
   989.5 1790.83   999.2 1792.22  1018.8 1792.47 1033.131794.218  1048.2 1799.02
#Mann= 9 ,-1 , 0
       0     .12       0  307.96    .016       0  374.27     .12       0
   431.2    .045       0   578.1     .12       0  856.85    .016       0
   961.6     .12       0   981.9    .016       0 1033.13     .12       0
Bank Sta=431.2,578.1
XS Rating Curve= 0 ,0
Exp/Cntr=0.3,0.1

Type RM Length L Ch R = 1 ,16568.9 ,612.5,614.3,616
XS GIS Cut Line= 2
     1837711.521      172896.919     1838442.717      172193.702
#Sta/Elev= 30
       0 1848.59    97.6 1819.05   126.8 1809.44   185.3 1785.54   263.4 1749.87
   273.1 1746.45   282.9 1744.65   321.9 1742.78  359.011738.493  404.34 1733.17
   458.5 1724.68   468.2 1723.96   487.7 1723.86   663.3 1724.47  668.751725.254
   673.1 1725.88   692.6 1732.64   702.3 1734.81   760.9 1744.52   790.1 1752.91
   799.9  1756.9   819.4 1767.31   829.1 1769.78   839.61770.644   868.2  1772.3
   877.9 1774.91   907.2  1792.3   916.9 1796.35   926.7 1798.55  1014.5 1807.28
#Mann= 7 ,-1 , 0
       0     .12       0  359.01    .016       0  404.34     .12       0
   468.2    .045       0   663.3     .12       0  668.75     .12       0
   839.6     .06       0
Bank Sta=468.2,663.3
XS Rating Curve= 0 ,0
Exp/Cntr=0.3,0.1

Type RM Length L Ch R = 1 ,15954.6 ,583.5,579.7,575.7
XS GIS Cut Line= 2
     1838115.431      173313.898     1838896.162      172622.829
#Sta/Elev= 30
       0 1816.31    29.5 1812.05      59 1805.69   196.7 1766.49   255.7 1746.24
  268.641743.122   285.2  1740.4   295.1 1737.64   301.81734.598   314.8 1728.29
   324.6 1724.92  327.681724.587   334.4 1723.86   580.3 1723.88     600 1725.11
   609.8 1726.83   649.2 1736.07   668.9 1739.74   678.7  1742.3   727.9 1759.49
   737.7 1761.66   806.6 1767.79   816.4 1769.46   826.2 1773.26   845.9 1784.69
   855.8 1788.98   865.6 1791.32   983.6 1798.54  1003.3 1798.62  1042.6 1796.46
#Mann= 6 ,-1 , 0
       0     .12       0  268.64    .016       0   301.8     .12       0
  327.68     .04       0   334.4    .045       0   580.3     .12       0
Bank Sta=334.4,580.3
XS Rating Curve= 0 ,0
Exp/Cntr=0.3,0.1

Type RM Length L Ch R = 1 ,15374.9 ,597.4,600,602.9
XS GIS Cut Line= 3
     1838442.042      173863.801     1838840.007       173430.46
     1839256.099      172976.914
#Sta/Elev= 30
       0 1758.31     9.8 1757.84      49 1753.98   117.7 1750.67  161.381747.277
  168.931746.396   205.9 1741.05   235.3  1736.2   245.2  1735.1   294.2 1731.51
   333.4 1729.49  347.591729.303     353 1729.38   372.6 1731.44   382.91730.987
   411.8 1728.52   451.1 1723.92   460.9 1723.46   470.7 1723.36   676.3 1723.46
   695.8 1724.63   764.2 1736.05   803.3 1740.36   852.1 1750.54  893.721757.039
   949.8 1763.98  1018.2 1769.18  1067.1  1773.7  1115.9  1776.8  1203.8 1781.26
#Mann= 8 ,-1 , 0
       0     .12       0  161.38    .016       0  168.93     .12       0
  347.59    .016       0   382.9     .12       0   460.9    .045       0
   676.3     .12       0  893.72    .016       0
Bank Sta=460.9,676.3
XS Rating Curve= 0 ,0
Exp/Cntr=0.3,0.1

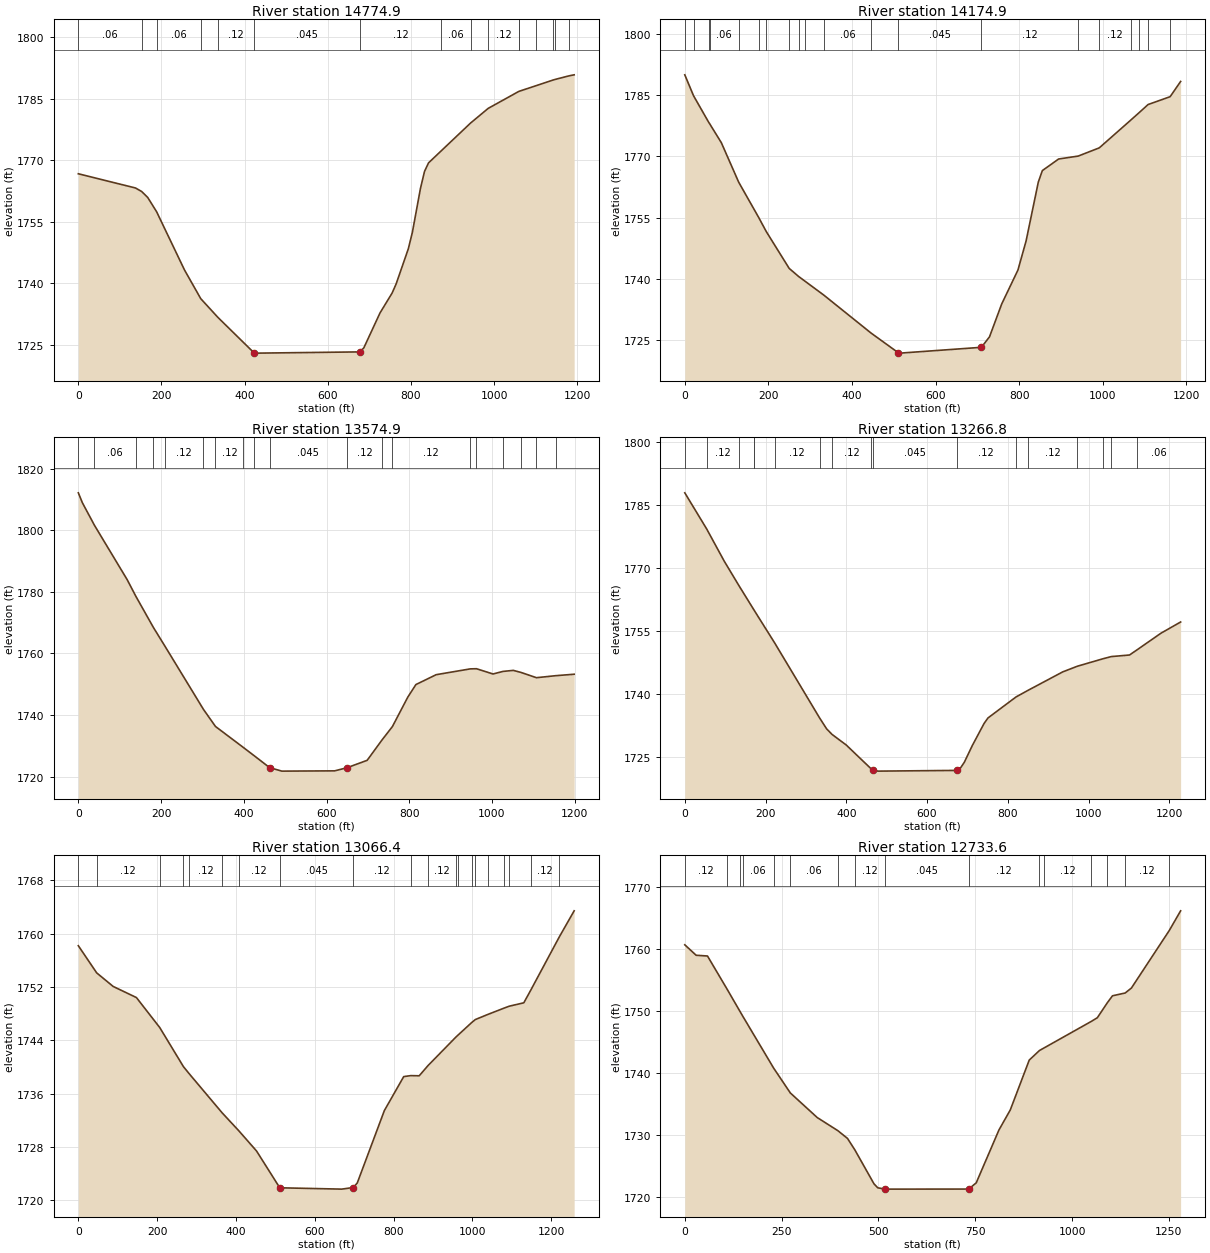
Type RM Length L Ch R = 1 ,14774.9 ,604.6,600,595.6
XS GIS Cut Line= 3
     1838846.867      174245.889      1839288.19      173826.467
     1839714.684      173428.042
#Sta/Elev= 30
       0 1766.72   137.5 1763.25  152.331762.395   166.9 1760.94  188.331757.447
   255.3 1743.26  294.411736.251  335.941731.656   422.3 1723.06   432.1 1722.96
   676.9 1723.26   686.6 1724.24   725.6 1732.77   754.8 1737.64   764.5 1739.88
   793.7 1748.43   803.4 1752.43   822.8 1763.12   832.6 1767.29   842.3 1769.38
  872.981772.332  943.431779.099  985.761782.674  1059.51786.819 1060.641786.858
 1100.451788.196 1142.45 1789.61 1147.29 1789.75 1180.071790.609  1192.5 1790.86
#Mann= 16 ,-1 , 0
       0     .06       0  152.33     .12       0  188.33     .06       0
  294.41    .016       0  335.94     .12       0   422.3    .045       0
   676.9     .12       0  872.98     .06       0  943.43    .016       0
  985.76     .12       0  1059.5     .06       0 1060.64     .12       0
 1100.45    .016       0 1142.45     .12       0 1147.29     .06       0
 1180.07     .12       0
Bank Sta=422.3,676.9
XS Rating Curve= 0 ,0
Exp/Cntr=0.3,0.1

Type RM Length L Ch R = 1 ,14174.9 ,596.3,600,603.2
XS GIS Cut Line= 3
     1839328.698      174706.315     1839679.986      174278.269
     1840087.708      173795.001
#Sta/Elev= 30
       0 1789.94   20.971784.817   57.511778.277   59.43 1777.99    87.4 1773.35
  128.94 1763.69  176.771755.062  194.861751.626  249.691742.613  272.341740.634
  288.091739.446  332.481736.087   445.9 1726.78  510.111722.038   514.9  1721.9
   709.4 1723.32   728.8 1725.87     758 1733.91   796.9 1742.22   816.4 1749.34
   845.6 1763.72   855.3 1766.53   894.2 1769.36  941.011770.075  991.431772.084
 1066.911778.883 1086.981780.713 1108.121782.673 1160.931784.594    1186 1788.32
#Mann= 20 ,-1 , 0
       0    .016       0   20.97     .06       0   57.51     .12       0
   59.43     .06       0  128.94    .016       0  176.77     .12       0
  194.86     .06       0  249.69     .12       0  272.34     .06       0
  288.09    .016       0  332.48     .06       0   445.9     .12       0
  510.11    .045       0   709.4     .12       0  941.01    .016       0
  991.43     .12       0 1066.91     .08       0 1086.98     .12       0
 1108.12    .016       0 1160.93     .12       0
Bank Sta=510.11,709.4
XS Rating Curve= 0 ,0
Exp/Cntr=0.3,0.1

Type RM Length L Ch R = 1 ,13574.9 ,309.1,308.1,306.3
XS GIS Cut Line= 3
     1839716.446      175087.923     1840119.952      174684.416
      1840564.02      174240.348
#Sta/Elev= 30
       0  1812.2     9.8 1808.98   38.911801.666   118.1 1783.98  138.981778.598
  181.47 1768.45  208.791762.497  302.541741.815  331.531736.276  399.171729.427
  425.071726.771   462.4  1722.9   491.9 1721.76   619.7 1721.85   649.2 1722.85
   698.2 1725.27  734.46 1731.95  759.331736.257   796.3 1745.77     816 1749.89
     865  1753.1  947.541754.987  962.471755.036  1002.4 1753.33 1026.511754.163
  1051.5  1754.5 1069.921753.841 1107.431752.123 1154.561752.781  1198.6 1753.25
#Mann= 19 ,-1 , 0
       0    .016       0   38.91     .06       0  138.98    .016       0
  181.47     .06       0  208.79     .12       0  302.54    .016       0
  331.53     .12       0  399.17     .06       0  425.07     .12       0
   462.4    .045       0   649.2     .12       0  734.46     .06       0
  759.33     .12       0  947.54     .06       0  962.47     .12       0
 1026.51    .016       0 1069.92     .06       0 1107.43    .016       0
 1154.56     .12       0
Bank Sta=462.4,649.2
XS Rating Curve= 0 ,0
Exp/Cntr=0.3,0.1

Type RM Length L Ch R = 1 ,13266.8 ,200.4,200.4,200.8
XS GIS Cut Line= 3
     1839941.636      175320.487     1840344.094      174895.368
     1840776.249      174419.462
#Sta/Elev= 30
       0 1787.86   54.441779.242    97.6 1771.64     1351765.673  171.671759.988
  172.081759.922  222.891752.158  334.151734.343   351.2  1731.8  364.721730.467
     400 1727.94  461.361722.308  467.291722.002   478.1 1721.74   673.1 1721.91
   682.8 1722.47   692.5 1723.86     712 1727.78   741.2 1733.04     751 1734.37
  820.381739.355  849.921740.917     936 1745.31  972.31 1746.66 1036.671748.457
  1056.31748.952  1101.6 1749.33 1121.351750.628  1179.5 1754.51  1228.2 1757.17
#Mann= 17 ,-1 , 0
       0     .12       0   54.44     .12       0     135     .06       0
  171.67     .12       0  172.08    .016       0  222.89     .12       0
  334.15    .016       0  364.72     .12       0  461.36     .06       0
  467.29    .045       0   673.1     .12       0  820.38     .06       0
  849.92     .12       0  972.31    .016       0 1036.67     .12       0
  1056.3    .016       0 1121.35     .06       0
Bank Sta=467.29,673.1
XS Rating Curve= 0 ,0
Exp/Cntr=0.3,0.1

Type RM Length L Ch R = 1 ,13066.4 ,334,332.9,332.1
XS GIS Cut Line= 3
     1840074.099      175471.347     1840513.365      175007.347
     1840929.644      174548.924
#Sta/Elev= 30
       0 1758.17   46.591754.097    88.5 1752.06   147.4  1750.4  206.561745.905
  266.771740.039  281.491738.969  364.891733.121  407.451730.414   452.2  1727.4
   511.2 1721.88   668.4 1721.68  697.691721.917   707.8  1722.6   776.6 1733.46
   825.7 1738.55  843.581738.696     865 1738.67  887.081740.182  958.321744.486
  964.151744.806  998.831746.686 1007.311747.097 1039.341747.873 1079.851748.803
 1093.621749.106  1130.4 1749.61 1147.651751.459  1220.4 1759.48  1258.2  1763.4
#Mann= 20 ,-1 , 0
       0     .06       0   46.59     .12       0  206.56    .016       0
  266.77     .06       0  281.49     .12       0  364.89    .016       0
  407.45     .12       0   511.2    .045       0  697.69     .12       0
  843.58    .016       0  887.08     .12       0  958.32     .08       0
  964.15     .12       0  998.83     .06       0 1007.31     .12       0
 1039.34     .06       0 1079.85     .12       0 1093.62    .016       0
 1147.65     .12       0  1220.4     .06       0
Bank Sta=511.2,697.69
XS Rating Curve= 0 ,0
Exp/Cntr=0.3,0.1

Type RM Length L Ch R = 1 ,12733.6 ,356.5,358.7,359
XS GIS Cut Line= 2
     1840326.641      175714.692     1841178.444      174758.904
#Sta/Elev= 30
       0 1760.74    29.3 1759.05    58.6 1758.93   109.41753.553  141.781750.052
  149.571749.216   229.51740.809  272.561736.797   342.1 1732.82  395.38  1730.7
   420.2 1729.45  439.211727.592   488.6 1722.11   498.4 1721.47     518 1721.26
     733 1721.27   752.5 1722.27   811.2 1730.82   840.5 1734.06   889.4 1742.11
  915.841743.661  928.521744.104 1050.031748.375  1065.3 1748.96 1091.031751.374
  1104.4  1752.5 1137.131752.952  1153.2 1753.75 1251.061763.056  1280.3 1766.23
#Mann= 16 ,-1 , 0
       0     .12       0   109.4     .06       0  141.78     .12       0
  149.57     .06       0   229.5    .016       0  272.56     .06       0
  395.38    .016       0  439.21     .12       0     518    .045       0
     733     .12       0  915.84     .06       0  928.52     .12       0
 1050.03     .08       0 1091.03    .016       0 1137.13     .12       0
 1251.06     .06       0
Bank Sta=518,733
XS Rating Curve= 0 ,0
Exp/Cntr=0.3,0.1

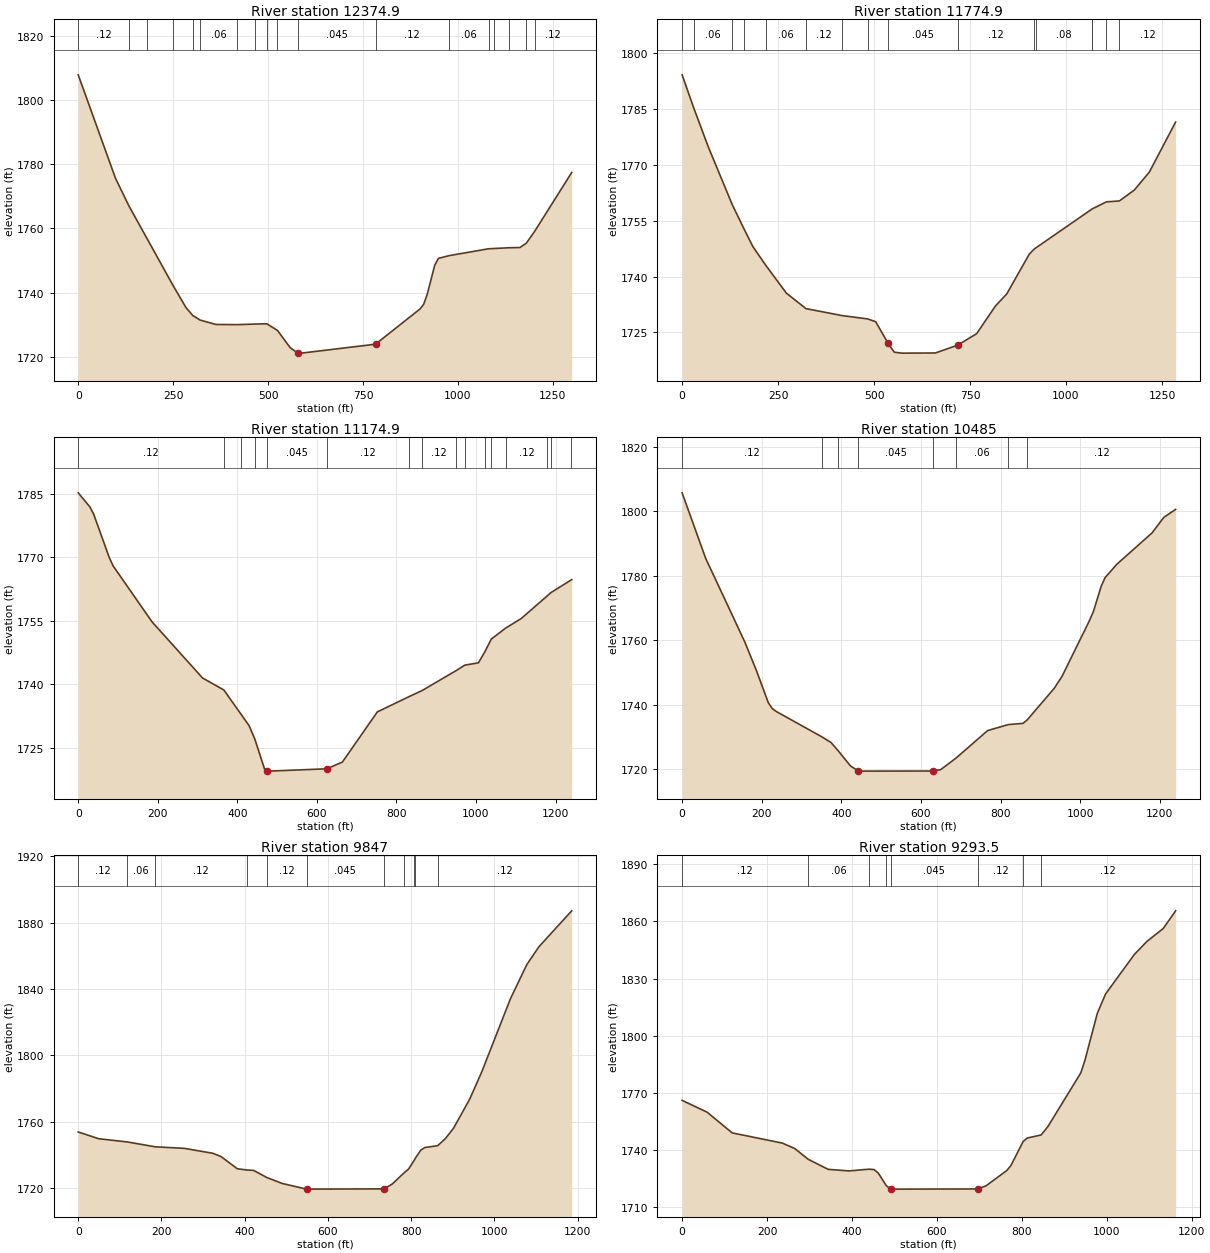
Type RM Length L Ch R = 1 ,12374.9 ,606.4,600,595.3
XS GIS Cut Line= 3
     1840571.416      175923.794     1841014.751      175480.462
     1841467.527      174983.176
#Sta/Elev= 30
       0 1807.84      98 1775.69  133.371767.047  181.46 1756.82  250.82 1742.02
   284.1 1735.32  301.521732.918  320.621731.497   362.5 1730.12  418.271730.054
  464.711730.238   496.61730.329  524.721728.258   558.4 1722.86     578 1721.23
   587.8 1721.19   782.9 1723.97   899.9 1734.93   909.6 1736.38   919.4 1739.64
   938.9 1748.61   948.6 1750.69  976.55 1751.54 1080.461753.678 1093.591753.756
 1135.361754.002    1163 1754.07 1179.781755.396 1202.141759.146  1299.5 1777.43
#Mann= 18 ,-1 , 0
       0     .12       0  133.37     .06       0  181.46     .12       0
  250.82    .016       0  301.52     .12       0  320.62     .06       0
  418.27     .12       0  464.71     .06       0   496.6    .016       0
  524.72     .12       0     578    .045       0   782.9     .12       0
  976.55     .06       0 1080.46     .12       0 1093.59     .06       0
 1135.36    .016       0 1179.78     .06       0 1202.14     .12       0
Bank Sta=578,782.9
XS Rating Curve= 0 ,0
Exp/Cntr=0.3,0.1

Type RM Length L Ch R = 1 ,11774.9 ,600.7,600,599.3
XS GIS Cut Line= 3
     1841159.439      176304.523     1841507.365      175814.264
     1841903.453      175256.139
#Sta/Elev= 30
       0 1794.19   30.221785.322    67.9 1774.91  130.41 1759.38  162.311752.587
   184.2 1748.09  217.481743.112   271.5 1735.58  322.621731.413  417.031729.537
  483.111728.651   504.2  1727.9  536.361722.133   552.7 1719.71   572.1 1719.46
   659.8  1719.5   718.5 1721.63   767.4  1724.7   816.3 1732.13   845.6 1735.34
   904.3 1746.03  917.341747.432  922.111747.763 1066.981758.093 1068.72 1758.21
 1105.371760.085 1138.971760.323    1178 1763.25  1217.1 1768.06  1285.6 1781.51
#Mann= 16 ,-1 , 0
       0     .12       0   30.22     .06       0  130.41     .12       0
  162.31    .016       0  217.48     .06       0  322.62     .12       0
  417.03     .06       0  483.11    .016       0  536.36    .045       0
   718.5     .12       0  917.34     .06       0  922.11     .08       0
 1066.98     .06       0 1068.72     .12       0 1105.37    .016       0
 1138.97     .12       0
Bank Sta=536.36,718.5
XS Rating Curve= 0 ,0
Exp/Cntr=0.3,0.1

Type RM Length L Ch R = 1 ,11174.9 ,681.5,689.9,698.2
XS GIS Cut Line= 3
     1841698.796      176594.339     1842012.562      176134.634
     1842398.175      175569.664
#Sta/Elev= 30
       0 1785.21    29.3 1781.89    39.1 1780.11    78.1  1769.9    87.9 1767.92
   185.5 1754.73   312.5 1741.46  366.131738.616  410.26 1732.76   429.6 1730.18
  443.861727.058   468.7 1719.86  475.541719.567   478.5 1719.44     625 1719.99
   664.1 1721.58     752 1733.44  832.621737.086  865.071738.514  950.29 1743.21
  971.781744.486  1006.1 1745.03 1022.641747.708 1038.311750.641 1074.631753.247
  1113.6  1755.5 1178.871760.835 1188.411761.629 1239.681764.647  1240.6  1764.7
#Mann= 16 ,-1 , 0
       0     .12       0  366.13     .07       0  410.26    .016       0
  443.86     .12       0  475.54    .045       0     625     .12       0
  832.62     .06       0  865.07     .12       0  950.29     .06       0
  971.78    .016       0 1022.64     .12       0 1038.31     .06       0
 1074.63     .12       0 1178.87     .06       0 1188.41     .12       0
 1239.68     .06       0
Bank Sta=475.54,625
XS Rating Curve= 0 ,0
Exp/Cntr=0.3,0.1

Type RM Length L Ch R = 1 ,10485   ,628.4,638.1,647.7
XS GIS Cut Line= 2
     1842126.809      176963.258     1843034.084      176118.127
#Sta/Elev= 30
       0 1805.71      59 1785.46   157.4 1759.51     187 1750.54   216.5 1740.67
   226.3 1738.88   236.2 1737.97  351.451730.063   373.9 1728.36  392.09 1725.78
   423.2 1721.04   442.8 1719.52   452.7 1719.46   629.8  1719.5   649.5 1719.91
  687.881723.468   767.6 1732.03  819.591733.887   856.1 1734.25  866.971735.324
   934.9 1745.12   954.5 1748.82  1023.4  1766.1  1033.3  1768.9    1053  1776.8
  1062.8 1779.44  1092.3 1783.58  1180.9 1793.32  1210.4 1798.13  1239.9 1800.57
#Mann= 8 ,-1 , 0
       0     .12       0  351.45    .016       0  392.09     .12       0
   442.8    .045       0   629.8     .12       0  687.88     .06       0
  819.59    .016       0  866.97     .12       0
Bank Sta=442.8,629.8
XS Rating Curve= 0 ,0
Exp/Cntr=0.3,0.1

Type RM Length L Ch R = 1 ,9847    ,553.8,553.5,553.1
XS GIS Cut Line= 2
     1842359.074      177388.242     1843404.187      176827.759
#Sta/Elev= 30
       0 1753.88      49 1749.83  118.081747.868  184.94 1744.95   254.8 1744.02
   323.4 1741.06     343  1739.1   382.2 1731.74  405.441730.953   421.4 1730.75
     4531726.482     490 1722.88   548.8 1719.45   735.1 1719.61   754.7 1722.55
  782.111729.026   793.9 1731.54  807.131736.723   810.3 1738.14   823.3 1742.95
   833.1 1744.53  863.661745.607   882.1 1749.84   901.7 1756.06   940.9 1773.72
   970.3 1790.44  1038.9 1834.29  1078.1 1854.76  1107.5  1865.6  1185.9 1887.12
#Mann= 11 ,-1 , 0
       0     .12       0  118.08     .06       0  184.94     .12       0
  405.44    .016       0     453     .12       0   548.8    .045       0
   735.1     .12       0  782.11     .06       0  807.13     .12       0
   810.3    .016       0  863.66     .12       0
Bank Sta=548.8,735.1
XS Rating Curve= 0 ,0
Exp/Cntr=0.3,0.1

Type RM Length L Ch R = 1 ,9293.5  ,519,518.6,518.3
XS GIS Cut Line= 3
     1842629.914      177877.967     1843155.375      177589.555
     1843648.678      177318.794
#Sta/Elev= 30
       0 1766.07      59 1759.85   117.9 1748.99   235.8 1743.64   265.3 1740.79
  296.691735.151   343.9 1729.85   393.1 1729.02  440.041729.937     452 1729.73
   461.8 1727.92  480.91 1721.25   491.3 1719.54   501.2 1719.46   696.4 1719.56
   715.8 1721.21   764.4  1729.2     774 1731.75  803.221744.544   812.9 1746.31
  845.331747.902   861.4 1752.31     939 1780.57   948.7 1787.25   977.8 1811.82
   997.2 1821.95  1065.1 1842.74  1094.2 1849.45    1133 1856.35  1162.1  1865.6
#Mann= 8 ,-1 , 0
       0     .12       0  296.69     .06       0  440.04    .016       0
  480.91     .12       0   491.3    .045       0   696.4     .12       0
  803.22    .016       0  845.33     .12       0
Bank Sta=491.3,696.4
XS Rating Curve= 0 ,0
Exp/Cntr=0.3,0.1

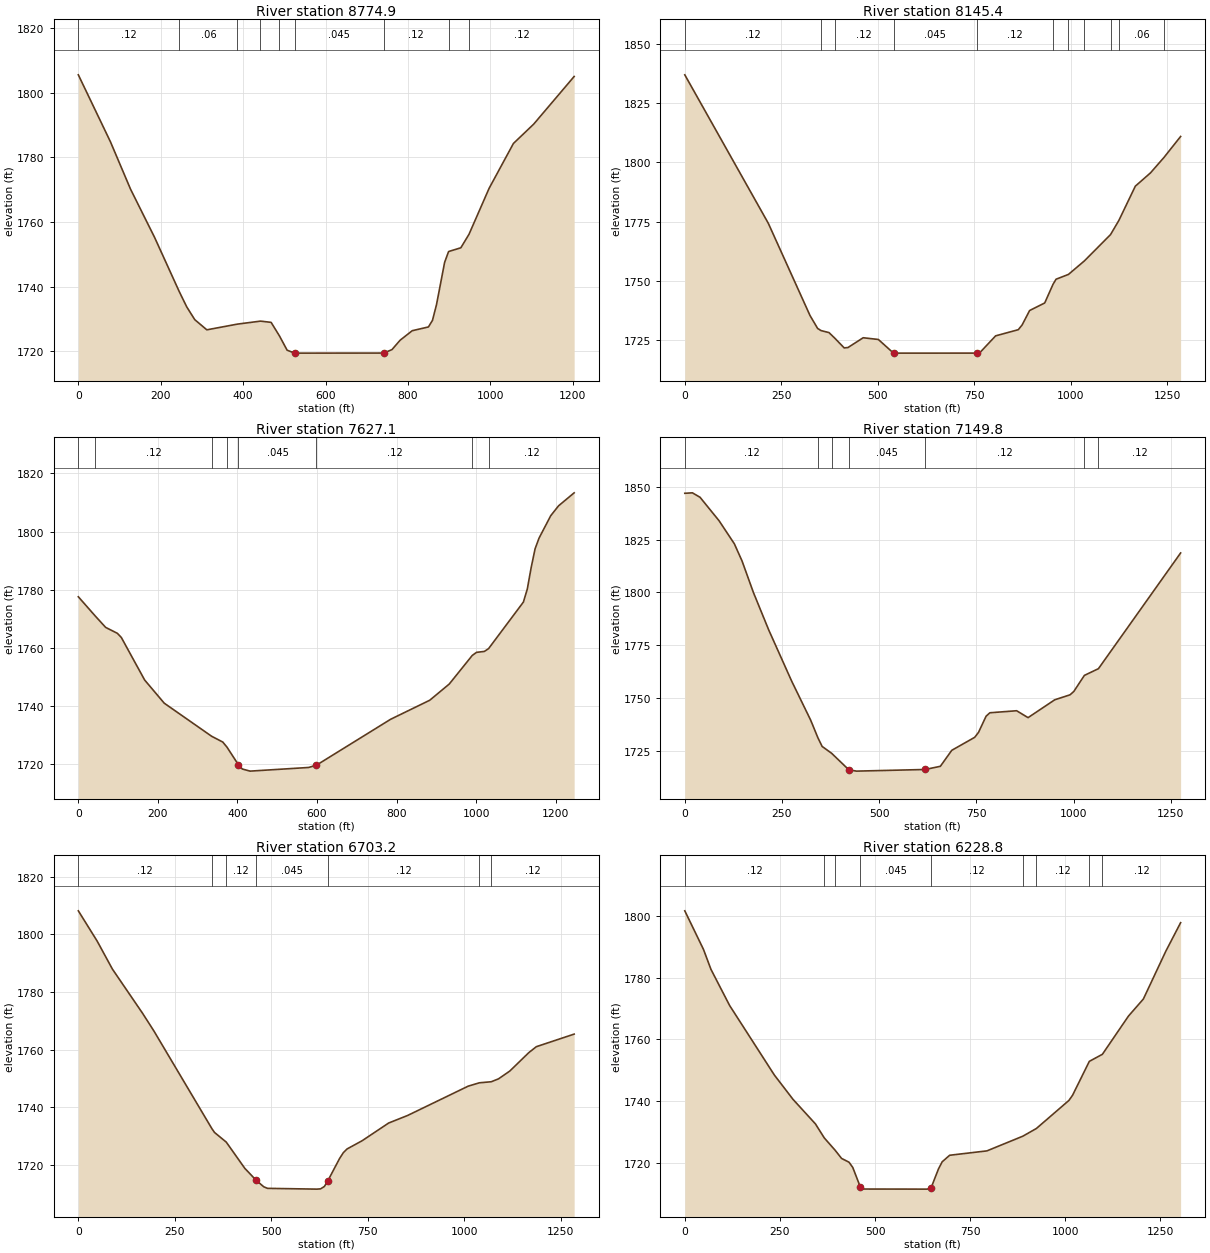
Type RM Length L Ch R = 1 ,8774.9  ,616.2,629.5,642.9
XS GIS Cut Line= 3
     1842892.977      178331.951     1843436.832      178026.675
     1843942.152       177743.03
#Sta/Elev= 30
       0 1805.55      78 1784.81   126.7 1770.17   185.2 1755.21   244.81738.508
   263.1 1733.74   282.6 1729.79   311.8 1726.65  386.091728.417     442 1729.34
   467.8 1728.96  488.151724.747   506.7 1720.34  524.881719.451   526.2 1719.44
   741.5 1719.46   761.2 1720.54   780.8 1723.43   810.3 1726.38   849.6 1727.54
   859.4 1729.58   869.2 1734.46   888.9 1747.54  898.511750.874   928.2 1752.03
  948.051756.215   996.9 1770.45  1055.8 1784.31  1104.9 1790.28  1203.2 1805.04
#Mann= 9 ,-1 , 0
       0     .12       0   244.8     .06       0  386.09     .12       0
     442    .016       0  488.15     .12       0  524.88    .045       0
   741.5     .12       0  898.51    .016       0  948.05     .12       0
Bank Sta=524.88,741.5
XS Rating Curve= 0 ,0
Exp/Cntr=0.3,0.1

Type RM Length L Ch R = 1 ,8145.4  ,518.8,518.3,517.7
XS GIS Cut Line= 3
     1843079.909      178697.431     1843682.184      178601.195
     1844349.356      178496.542
#Sta/Elev= 30
       0 1836.89   216.4 1774.27   324.6 1735.32   344.3 1729.88  353.071728.976
   373.8 1728.12  388.251725.856   413.2 1721.66     423 1721.82   462.4 1725.95
   501.7 1725.22     541 1719.47   550.9 1719.46   756.7 1719.47   766.5 1719.96
   805.7 1726.75   864.4 1729.35   874.2  1731.3   893.8 1737.44   932.9 1740.62
  954.371748.463   962.3 1750.64  994.511752.681 1035.721758.373 1103.581769.481
 1125.191775.467  1167.8 1789.91    1207  1795.5 1241.85 1801.99  1285.2 1810.88
#Mann= 11 ,-1 , 0
       0     .12       0  353.07    .016       0  388.25     .12       0
     541    .045       0   756.7     .12       0  954.37    .016       0
  994.51     .12       0 1035.72     .06       0 1103.58     .12       0
 1125.19     .06       0 1241.85     .12       0
Bank Sta=541,756.7
XS Rating Curve= 0 ,0
Exp/Cntr=0.3,0.1

Type RM Length L Ch R = 1 ,7627.1  ,478.4,477.3,476
XS GIS Cut Line= 2
     1843206.787      179195.534     1844434.943      178983.132
#Sta/Elev= 30
       0 1777.52   42.731770.861    68.7 1766.97    98.1 1764.93     108 1763.51
   166.8 1748.82   215.9 1740.86  335.05 1729.46   363.1 1727.46  373.531725.736
   402.4 1719.64   412.2 1718.17   431.8 1717.44     579  1718.7   598.7  1719.5
   785.1 1735.31   883.3 1741.86   932.3 1747.43  990.241757.302    1001 1758.37
  1020.7 1758.69 1031.331759.664  1118.8  1775.7  1128.6 1780.17  1138.4 1787.63
  1148.2 1794.06  1158.1 1797.72  1187.5 1805.45  1207.1 1808.85  1246.4 1813.34
#Mann= 8 ,-1 , 0
       0    .016       0   42.73     .12       0  335.05    .016       0
  373.53     .12       0   402.4    .045       0   598.7     .12       0
  990.24    .016       0 1031.33     .12       0
Bank Sta=402.4,598.7
XS Rating Curve= 0 ,0
Exp/Cntr=0.3,0.1

Type RM Length L Ch R = 1 ,7149.8  ,446.2,446.6,447
XS GIS Cut Line= 2
     1843304.586      179662.527     1844553.744      179405.608
#Sta/Elev= 30
       0 1846.82    19.6 1847.04    39.2 1844.94    88.3 1833.83   127.5 1822.96
   147.2 1814.89   176.6 1799.94   215.8 1782.34   274.7 1758.22   323.7 1739.75
  342.511731.353   353.2 1727.33  377.651724.083   421.8 1716.31   441.4 1715.66
     618 1716.43   657.3 1717.93   686.7 1725.49   745.6 1731.61   755.4 1733.93
     775  1741.6   784.8 1743.21   853.5 1744.17   882.9 1740.91   951.6 1749.34
   990.8 1751.68  1000.6 1753.28 1027.781760.855  1063.91764.018  1275.3 1818.65
#Mann= 7 ,-1 , 0
       0     .12       0  342.51    .016       0  377.65     .12       0
   421.8    .045       0     618     .12       0 1027.78    .016       0
  1063.9     .12       0
Bank Sta=421.8,618
XS Rating Curve= 0 ,0
Exp/Cntr=0.3,0.1

Type RM Length L Ch R = 1 ,6703.2  ,473.4,474.4,475.3
XS GIS Cut Line= 2
     1843389.501      180089.421     1844652.515      179853.028
#Sta/Elev= 30
       0  1808.2      49 1797.64    88.3 1787.96   166.8 1772.54   196.2 1766.38
  346.43 1732.46   353.1 1731.18   383.41727.842   431.6 1718.71     461 1714.57
   480.6 1712.32   490.4 1711.78     618 1711.51   627.8  1711.6   637.6 1712.43
  646.491714.371   676.8 1722.08   686.6 1724.15   696.4 1725.46   735.7 1728.34
   804.3 1734.48   853.4  1737.1  1010.3 1747.28 1039.34 1748.45 1070.151748.816
  1088.8 1749.81  1118.2 1752.53  1167.2  1758.9  1186.9 1760.99    1285 1765.37
#Mann= 7 ,-1 , 0
       0     .12       0  346.43    .016       0   383.4     .12       0
     461    .045       0  646.49     .12       0 1039.34    .016       0
 1070.15     .12       0
Bank Sta=461,646.49
XS Rating Curve= 0 ,0
Exp/Cntr=0.3,0.1

Type RM Length L Ch R = 1 ,6228.8  ,511,515.3,519.7
XS GIS Cut Line= 3
     1843466.402      180543.024     1843989.612      180459.258
     1844753.385      180336.978
#Sta/Elev= 30
       0 1801.75    49.1 1789.24    68.7 1782.78   117.8 1771.04   235.5 1748.46
   284.6 1740.56   343.4 1732.62   366.61728.076  395.221724.061   412.1 1721.41
   431.8 1720.18   441.6 1718.47   461.2 1712.21     471 1711.48   637.6 1711.45
   647.4 1711.85     667 1718.04   676.7 1720.33   696.3 1722.44   794.2 1723.86
  888.631728.627  924.371731.137  1009.6 1740.21  1019.4 1741.92  1063.41752.904
 1097.721755.195  1166.3  1767.6  1205.5 1773.14  1264.2 1788.58  1303.4  1797.9
#Mann= 9 ,-1 , 0
       0     .12       0   366.6    .016       0  395.22     .12       0
   461.2    .045       0   647.4     .12       0  888.63    .016       0
  924.37     .12       0  1063.4    .016       0 1097.72     .12       0
Bank Sta=461.2,647.4
XS Rating Curve= 0 ,0
Exp/Cntr=0.3,0.1