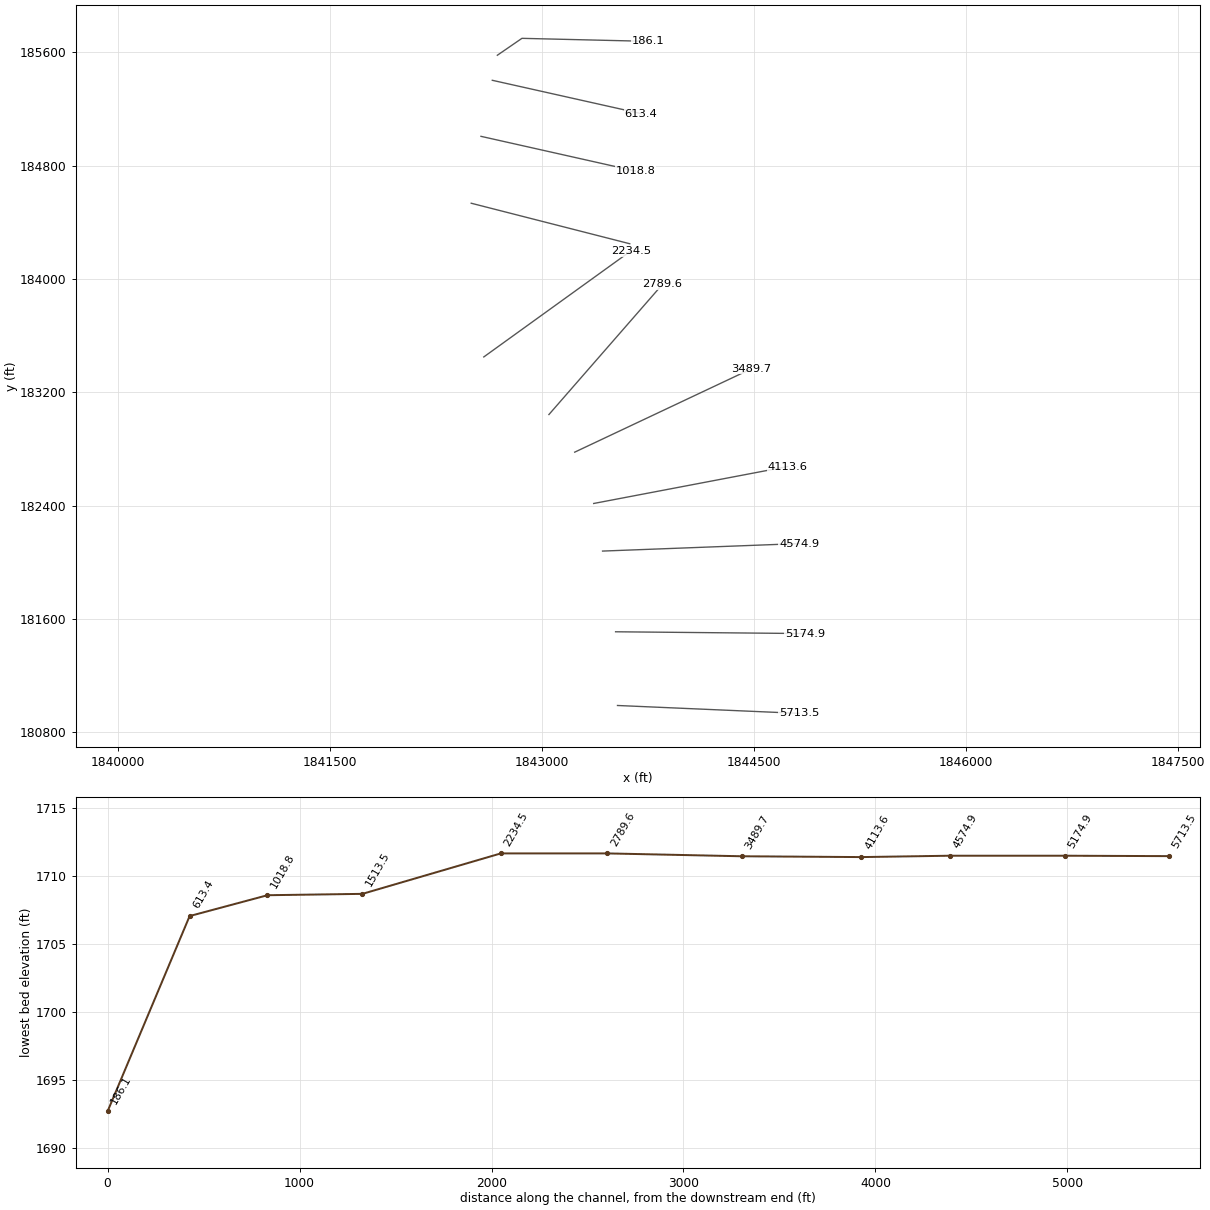
HEC-RAS study TYGARTVR2.prj: TYGARTVR2

--- TYGARTVR2.g01 (geometry) --- (continued)

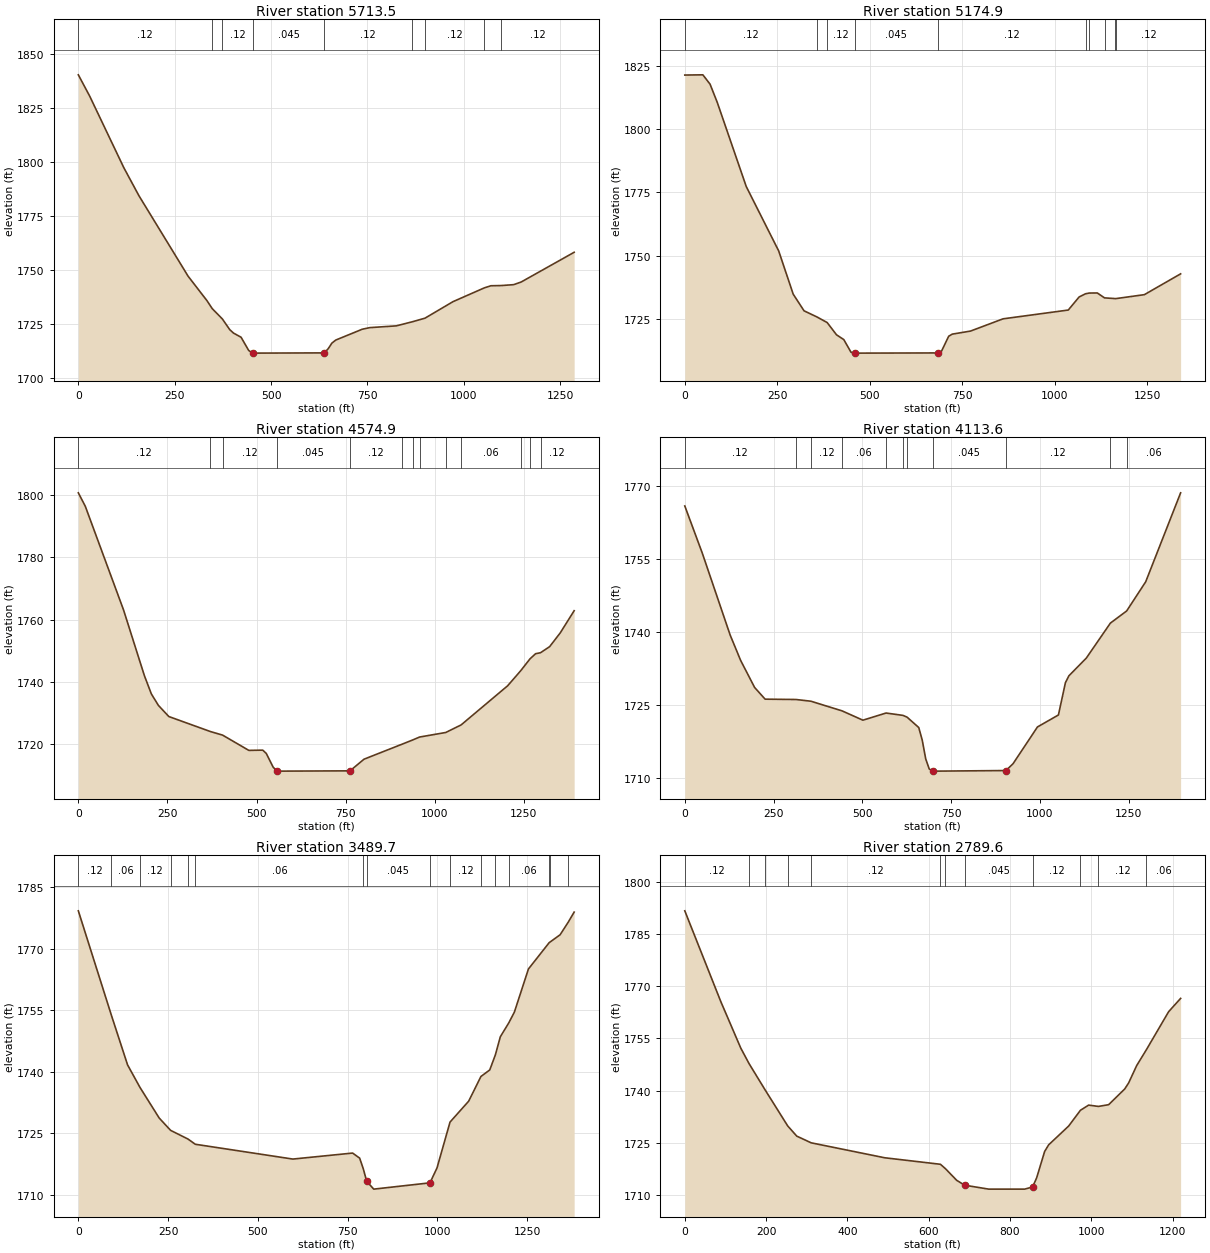
Type RM Length L Ch R = 1 ,5713.5  ,537.3,538.6,539.9
XS GIS Cut Line= 2
     1843533.359      180989.407     1844818.406      180933.713
#Sta/Elev= 30
       0 1840.45    29.5 1830.56   117.8 1797.47   157.1 1784.44   284.7 1747.11
   333.8 1735.73  347.321732.067  373.691727.257   392.8 1722.31   402.6 1720.72
   422.2 1718.79   441.8  1712.7   451.7 1711.43  453.931711.435   638.2 1711.54
     648 1713.43   657.8 1716.08   667.7 1717.48   736.4  1722.5     756 1723.25
   824.8 1724.07  865.61 1725.93  899.221727.629     972  1735.3 1053.421741.699
  1070.2 1742.66 1096.431742.753  1129.2 1743.17  1148.8  1744.4  1286.2 1758.18
#Mann= 9 ,-1 , 0
       0     .12       0  347.32    .016       0  373.69     .12       0
  453.93    .045       0   638.2     .12       0  865.61     .06       0
  899.22     .12       0 1053.42    .016       0 1096.43     .12       0
Bank Sta=453.93,638.2
XS Rating Curve= 0 ,0
Exp/Cntr=0.3,0.1

Type RM Length L Ch R = 1 ,5174.9  ,598.2,600,601.8
XS GIS Cut Line= 3
     1843519.933      181509.685     1844086.171      181504.346
     1844859.637      181497.053
#Sta/Elev= 30
       0 1821.24    48.8 1821.33    68.3 1817.64    87.9 1810.38     166 1777.25
   253.8 1751.78   292.9 1734.75   322.2 1728.17  357.56 1725.71  384.731723.532
     410 1718.69   429.6 1716.81   449.1 1711.82   458.9 1711.46  684.821711.536
   693.6 1712.19   713.1 1718.13   722.9 1718.96   771.9 1720.16     860    1725
  1036.2 1728.47  1065.6 1733.64 1082.931734.894 1093.241735.177  1114.6 1735.21
 1134.171733.273 1163.711732.983 1166.361733.015  1241.8 1734.54  1339.8 1742.76
#Mann= 10 ,-1 , 0
       0     .12       0  357.56    .016       0  384.73     .12       0
   458.9    .045       0  684.82     .12       0 1082.93     .06       0
 1093.24     .12       0 1134.17    .016       0 1163.71     .06       0
 1166.36     .12       0
Bank Sta=458.9,684.82
XS Rating Curve= 0 ,0
Exp/Cntr=0.3,0.1

Type RM Length L Ch R = 1 ,4574.9  ,454.6,461.3,468
XS GIS Cut Line= 3
     1843427.705      182079.304     1844081.424      182104.171
     1844817.905      182132.186
#Sta/Elev= 30
       0 1800.57    19.5 1796.28   126.9 1763.06   185.5 1741.98     205 1736.16
   224.6 1732.52   253.9 1728.94  370.371724.143  404.811722.991   478.4  1718.1
   517.5 1718.18   527.3 1717.13   546.8  1712.7   556.6  1711.6   566.3 1711.46
   762.3 1711.55   801.6 1715.28  907.721720.055   938.91721.474  957.621722.377
 1030.971723.834 1073.97 1726.25  1204.5 1738.78  1241.2  1743.6  1267.21747.398
  1283.1 1749.06 1296.781749.369  1322.4 1751.32  1351.9 1755.68  1391.2 1762.82
#Mann= 13 ,-1 , 0
       0     .12       0  370.37    .016       0  404.81     .12       0
   556.6    .045       0   762.3     .12       0  907.72     .06       0
   938.9     .12       0  957.62     .06       0 1030.97     .12       0
 1073.97     .06       0  1241.2     .12       0  1267.2    .016       0
 1296.78     .12       0
Bank Sta=556.6,762.3
XS Rating Curve= 0 ,0
Exp/Cntr=0.3,0.1

Type RM Length L Ch R = 1 ,4113.6  ,615.3,623.8,632.4
XS GIS Cut Line= 2
     1843365.118      182415.294     1844736.825      182675.877
#Sta/Elev= 30
       0 1765.86    49.2 1756.18   127.8 1739.32   157.3 1734.11   196.6 1728.56
   226.2 1726.15  312.961726.082  355.05 1725.73  442.891723.745   501.5 1721.83
  566.73  1723.3  614.261722.818  625.791722.462   658.8 1720.32   668.6 1717.74
   678.4 1713.88   688.3  1711.8   698.1 1711.37     708 1711.36  904.281711.478
   924.3 1712.88   993.1 1720.44  1052.1  1722.9  1071.8 1729.54  1081.6 1730.95
  1130.8 1734.61 1198.471741.787 1244.231744.278  1297.9 1750.28  1396.2 1768.56
#Mann= 11 ,-1 , 0
       0     .12       0  312.96    .016       0  355.05     .12       0
  442.89     .06       0  566.73     .12       0  614.26     .06       0
  625.79     .12       0   698.1    .045       0  904.28     .12       0
 1198.47    .016       0 1244.23     .06       0
Bank Sta=698.1,904.28
XS Rating Curve= 0 ,0
Exp/Cntr=0.3,0.1

Type RM Length L Ch R = 1 ,3489.7  ,686.3,700.2,714.4
XS GIS Cut Line= 2
      1843230.64      182777.507      1844479.89       183365.52
#Sta/Elev= 30
       0 1779.19   92.351753.687   137.1 1741.68  171.451736.223   225.2 1728.73
  256.911725.734  305.531723.607  325.811722.345   597.3 1718.74   763.8  1720.2
   783.4 1718.97   793.61716.342     803 1713.33   822.6 1711.42   979.2 1712.95
   998.8 1716.58 1035.08 1727.75    1087 1732.84  1121.11738.846  1145.7 1740.45
 1161.34 1744.12  1175.1 1748.52 1198.681751.906  1214.2 1754.52  1253.4 1765.03
  1311.31771.454 1312.631771.529  1341.6 1773.36 1364.23 1776.43  1380.7 1778.88
#Mann= 16 ,-1 , 0
       0     .12       0   92.35     .06       0  171.45     .12       0
  256.91    .016       0  305.53     .12       0  325.81     .06       0
   793.6     .12       0     803    .045       0   979.2     .06       0
 1035.08     .12       0  1121.1    .016       0 1161.34     .12       0
 1198.68     .06       0  1311.3     .12       0 1312.63     .06       0
 1364.23     .12       0
Bank Sta=803,979.2
XS Rating Curve= 0 ,0
Exp/Cntr=0.3,0.1

Type RM Length L Ch R = 1 ,2789.6  ,562.3,555,545.5
XS GIS Cut Line= 2
     1843048.348      183043.132     1843851.067      183961.425
#Sta/Elev= 30
       0 1791.69    88.5  1765.6   137.7  1752.2  158.021747.752  197.981740.098
  253.221729.805   275.4 1726.88  310.851724.952   491.8 1720.65   628.81718.777
   641.11717.524   668.9 1714.16   688.5 1712.76   747.6 1711.63   836.1 1711.63
   855.7 1712.26   865.6  1714.9   885.2 1722.47   895.1 1724.37   944.3 1729.78
  973.231734.308   993.4  1735.8 1017.451735.424  1042.6 1735.92    1082 1740.42
  1091.8 1742.17  1111.5 1747.15 1135.561751.752  1190.2 1762.67  1219.7  1766.5
#Mann= 12 ,-1 , 0
       0     .12       0  158.02     .06       0  197.98     .12       0
  253.22    .016       0  310.85     .12       0   628.8     .06       0
   641.1     .12       0   688.5    .045       0   855.7     .12       0
  973.23    .016       0 1017.45     .12       0 1135.56     .06       0
Bank Sta=688.5,855.7
XS Rating Curve= 0 ,0
Exp/Cntr=0.3,0.1

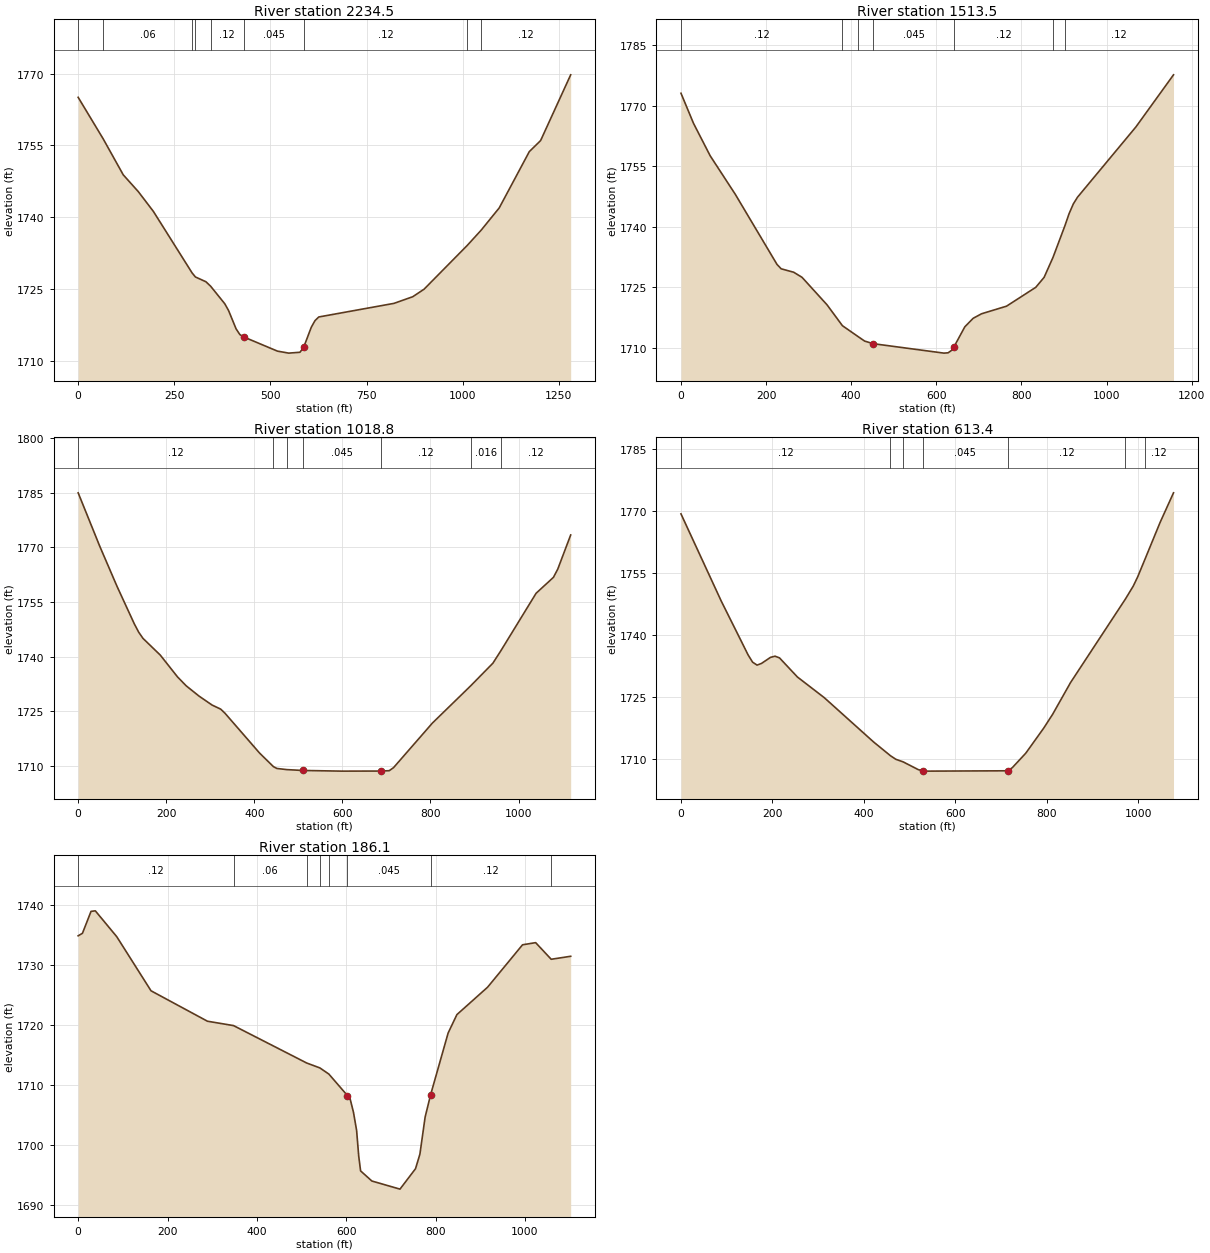
Type RM Length L Ch R = 1 ,2234.5  ,753.6,721.1,689.8
XS GIS Cut Line= 2
       1842587.6      183449.655     1843627.424      184197.599
#Sta/Elev= 30
       0 1765.05   65.051756.382   117.3 1748.86   156.4 1745.36   195.6 1741.23
  296.311728.381  304.921727.538   332.4 1726.53  344.751725.583   381.3 1721.94
   391.1 1720.54   410.7  1716.7   420.4 1715.52   430.2 1715.02   518.2 1712.05
   547.6 1711.63   576.9 1711.81   586.7 1712.89   606.2 1717.02     616 1718.42
   625.8 1719.18   821.3 1722.02   870.2 1723.41   899.6 1724.98 1011.851734.118
 1048.141737.312  1095.1 1741.96  1173.3 1753.71  1202.7 1756.02  1280.9 1769.75
#Mann= 9 ,-1 , 0
       0     .12       0   65.05     .06       0  296.31     .12       0
  304.92    .016       0  344.75     .12       0   430.2    .045       0
   586.7     .12       0 1011.85    .016       0 1048.14     .12       0
Bank Sta=430.2,586.7
XS Rating Curve= 0 ,0
Exp/Cntr=0.3,0.1

Type RM Length L Ch R = 1 ,1513.5  ,493.6,494.6,495.7
XS GIS Cut Line= 2
     1842498.567      184534.573      1843619.91      184248.697
#Sta/Elev= 30
       0 1773.14    29.4 1765.68    68.6 1757.62   127.5 1748.08   225.6 1730.67
   235.4 1729.58   264.8 1728.73   284.4 1727.47   343.2 1720.64  379.241715.473
  414.91 1712.85   431.5 1711.65   451.1 1711.01   617.8 1708.66   627.6 1708.74
   637.4 1709.46  641.561710.254   666.9 1715.19   686.5  1717.3   706.1 1718.42
   764.9 1720.31   833.6 1724.99   853.2 1727.46  874.051732.408  901.761740.178
     912  1743.3   921.8 1745.67   931.6 1747.34    1069  1764.8  1157.2 1777.71
#Mann= 7 ,-1 , 0
       0     .12       0  379.24    .016       0  414.91     .12       0
   451.1    .045       0  641.56     .12       0  874.05    .016       0
  901.76     .12       0
Bank Sta=451.1,641.56
XS Rating Curve= 0 ,0
Exp/Cntr=0.3,0.1

Type RM Length L Ch R = 1 ,1018.8  ,405.5,405.5,405.5
XS GIS Cut Line= 2
     1842567.615      185006.751     1843658.921      184762.111
#Sta/Elev= 30
       0 1784.93      49 1770.28    88.3 1759.25   127.5 1748.97   137.4  1746.7
   147.2 1744.99   186.4 1740.41   225.6 1734.42   245.3 1731.97   274.7 1729.13
   304.1 1726.69   323.7 1725.57   333.6 1724.42     412 1713.51  443.521709.782
   451.3 1709.29  473.831708.976   510.1 1708.74   598.4 1708.56   686.7 1708.58
   706.4 1708.68   716.2 1709.52   804.5 1721.76  891.561731.997   941.8 1738.18
  960.591741.735  1039.9 1757.37  1079.2 1761.73    1089 1763.97  1118.4 1773.36
#Mann= 7 ,-1 , 0
       0     .12       0  443.52    .016       0  473.83     .12       0
   510.1    .045       0   686.7     .12       0  891.56    .016       0
  960.59     .12       0
Bank Sta=510.1,686.7
XS Rating Curve= 0 ,0
Exp/Cntr=0.3,0.1

Type RM Length L Ch R = 1 ,613.4   ,419.8,427.3,434.5
XS GIS Cut Line= 2
     1842647.637      185402.378     1843698.606      185167.587
#Sta/Elev= 30
       0 1769.29    88.1 1748.17   146.8 1735.15   156.6  1733.4   166.4 1732.69
   176.2 1733.11   195.8 1734.57   205.6 1734.85   215.4 1734.44   254.5 1729.82
   313.3 1724.81     421  1714.1  457.951710.764   469.9 1709.89  485.751709.268
   518.9 1707.39   528.6  1707.1   538.4 1707.03   714.6 1707.11   724.4 1707.86
   753.8 1711.36     793 1717.42   812.6 1720.78   851.7 1728.45  971.931748.715
   988.8  1751.8   998.6 1754.05 1014.271758.252  1047.5  1767.2  1076.9 1774.39
#Mann= 7 ,-1 , 0
       0     .12       0  457.95    .016       0  485.75     .12       0
   528.6    .045       0   714.6     .12       0  971.93    .016       0
 1014.27     .12       0
Bank Sta=528.6,714.6
XS Rating Curve= 0 ,0
Exp/Cntr=0.3,0.1

Type RM Length L Ch R = 1 ,186.1   ,183.2,186.1,189
XS GIS Cut Line= 3
     1842683.333      185579.073     1842857.376      185698.514
     1843748.493      185677.297
#Sta/Elev= 30
       0  1734.9     9.6 1735.32    28.8 1738.97    38.4 1739.06    86.4 1734.75
   163.1 1725.74   289.4 1720.67  347.85 1719.94  511.571713.709  541.11 1712.89
  561.141711.869   602.9 1708.28  608.83 1707.72  616.31 1705.49  623.32 1702.47
     628 1698.22  632.21 1695.74  657.45 1694.05   720.4  1692.7  755.16  1696.1
  764.98 1698.52  776.67  1704.7     789 1708.43   828.2 1718.71   847.8 1721.77
   916.4 1726.33   994.7  1733.4  1024.1 1733.76  1058.91730.989  1102.5 1731.49
#Mann= 8 ,-1 , 0
       0     .12       0  347.85     .06       0  511.57     .12       0
  541.11    .016       0  561.14     .12       0   602.9    .045       0
     789     .12       0  1058.9     .06       0
Bank Sta=602.9,789
XS Rating Curve= 0 ,0
Exp/Cntr=0.3,0.1

Chan Stop Cuts=-1
Use User Specified Reach Order=0
Composite Channel Slope=5